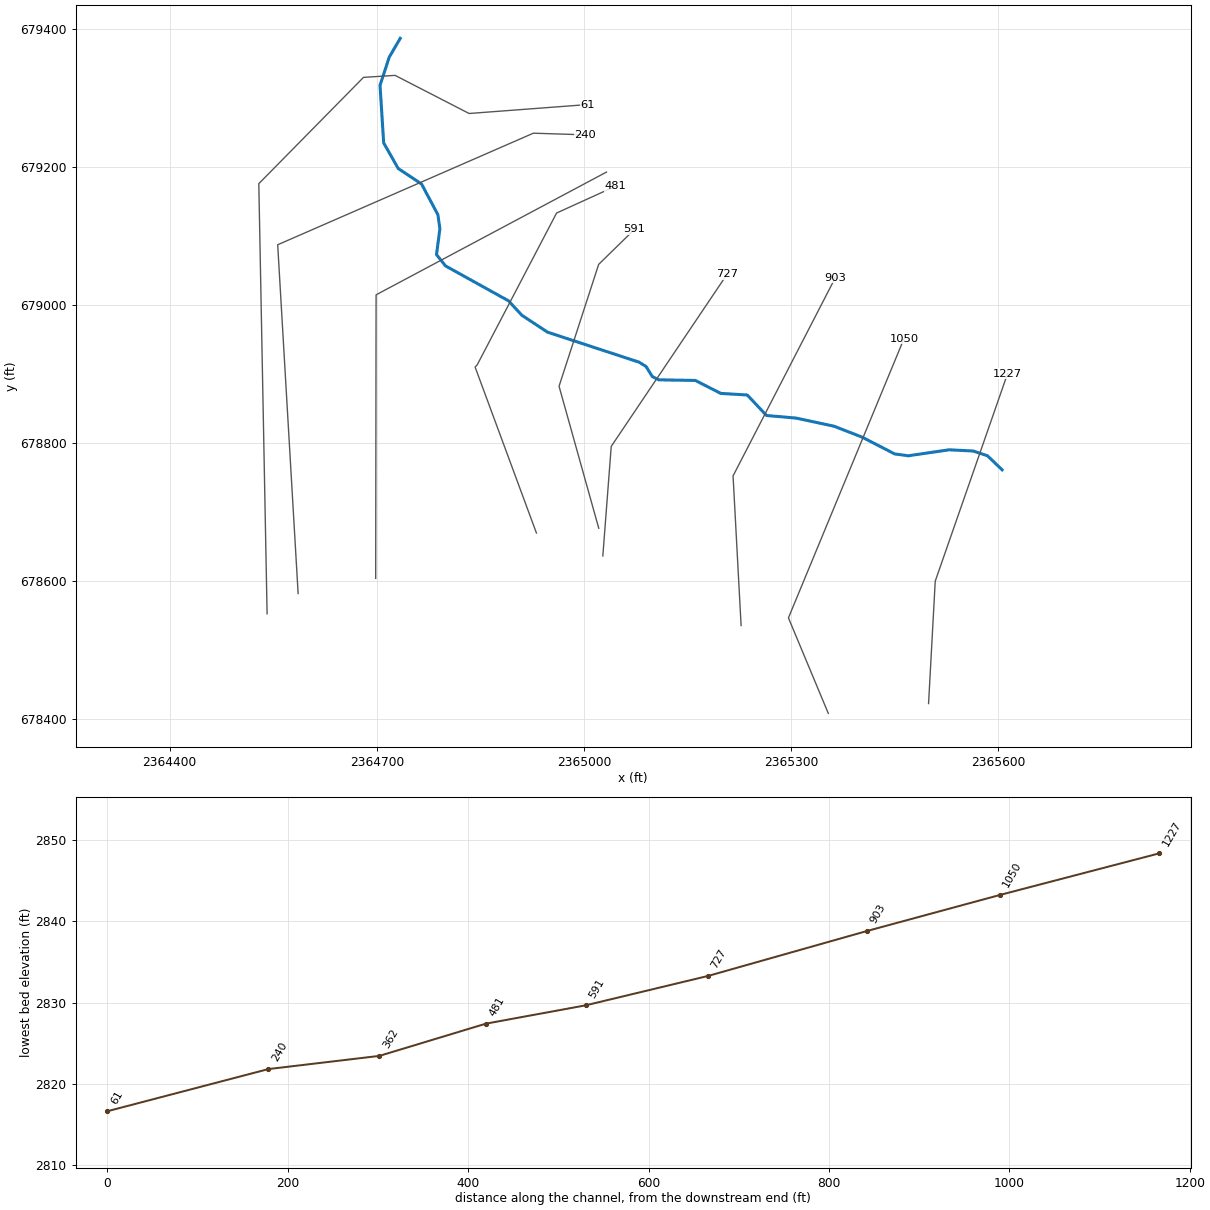
--- LAURELFKT1.prj (project) ---

Proj Title=LAURELFKT1
Current Plan=p01
Default Exp/Contr=0,0
English Units
Geom File=g01
Flow File=f01
Plan File=p01
BEGIN DESCRIPTION:
----------MODEL BY WOOD PLC 2022----------
AFH study
Randolph County, WV
HEC-RAS Version: RAS 6.2
Vertical Datum: NAVD88
Projection: NAD 1983 StatePlane West Virginia S FIPS 4702 (US Feet)
Terrain: 1-meter LIDAR (FEMA Region III 3DEP collected 2016-2018)
Land Use: 2019 NLCD
Hydrologic Method:
WV SIR2010-5033 regression equations
Additional Model Notes:
None
END DESCRIPTION:
DSS Export Rating Curves= 0
DSS Export Rating Curve Sorted= 0
DSS Export Volume Flow Curves= 0
DXF OffsetX= 0
DXF OffsetY= 0
DXF ScaleX= 0
DXF ScaleY= 0

--- LAURELFKT1.p01 (plan) ---

Plan Title=Floodplain
Program Version=6.20
Short Identifier=Floodplain
Geom File=g01
Flow File=f01
Subcritical Flow
K Sum by GR= 0
Std Step Tol= 0.01
Critical Tol= 0.01
Num of Std Step Trials= 20
Max Error Tol= 0.3
Flow Tol Ratio= 0.001
Split Flow NTrial= 30
Split Flow Tol= 0.02
Split Flow Ratio= 0.02
Log Output Level= 0
Friction Slope Method= 1
Unsteady Friction Slope Method= 2
Unsteady Bridges Friction Slope Method= 1
Parabolic Critical Depth
Global Vel Dist= 0 , 0 , 0
Global Log Level= 0
CheckData=False
Encroach Param=-1 ,0,0, 0
Mapping Interval=1HOUR
Computation Time Step Use Courant=        0
Computation Time Step Use Time Series=    0
Computation Time Step Count To Double=0
Computation Time Step Max Doubling=0
Computation Time Step Max Halving=0
Computation Time Step Residence Courant=0
Run HTab= 0
Run UNet= 0
Run Sediment= 0
Run PostProcess= 0
Run WQNet= 0
Run RASMapper=-1
UNET Theta= 0
UNET Theta Warmup= 0
UNET ZTol= 0
UNET ZSATol= 0
UNET MxIter= 0
UNET Max Iter WO Improvement= 0
UNET MaxInSteps= 0
UNET DtIC= 0
UNET DtMin= 0
UNET MaxCRTS= 0
UNET WFStab= 0
UNET SFStab= 0
UNET WFX= 1
UNET SFX= 1
UNET Gravity=32.174
UNET 1D Methodology=Finite Difference
UNET DSS MLevel= 1
UNET Pardiso=0
UNET DZMax Abort= 0
UNET Use Existing IB Tables= 0
UNET Froude Reduction=False
UNET Froude Limit= 0
UNET Froude Power= 0
UNET D1 Cores= 0
UNET WindReference=Eulerian
UNET WindDragFormulation=Hsu (1988)
UNET D2 Coriolis=0
UNET D2 Cores= 0
UNET D2 Theta= 1
UNET D2 Theta Warmup= 1
UNET D2 Z Tol= 0.01
UNET D2 Volume Tol= 0.01
UNET D2 Max Iterations= 20
UNET D2 Equation= 0
UNET D2 RampUpFraction=0.1
UNET D2 TimeSlices= 1
UNET D2 Turbulence Formulation=Non-Conservative (original)
UNET D2 Eddy Viscosity=0.3
UNET D2 Transverse Eddy Viscosity=0.1
UNET D2 Smagorinsky Mixing=0
UNET D2 BCVolumeCheck=0
UNET D2 Cores=0
UNET D2 SolverType=PARDISO (Direct)
UNET D2 Minimum Iterations= 2147483647
UNET D2 Maximum Iterations= 2147483647
UNET D2 Restart Number= 10
UNET D2 Relaxation Coeff=1.3
UNET D2 SOR Precondition Iterations= 10
UNET D2 ILUT Maximum Fill= 8
UNET D2 ILUT Tolerance=1E-08
UNET D1D2 MaxIter= 0
UNET D1D2 ZTol=0.01
UNET D1D2 QTol=0.1
UNET D1D2 MinQTol=1
Write IC File= 0
Write IC File at Fixed DateTime=0
Write IC File at Sim End=0
Echo Input=False
Echo Parameters=False
Echo Output=False
Write Detailed= 0
HDF Write Warmup=0
HDF Write Time Slices=0
HDF Flush=0
HDF Compression= 1
HDF Chunk Size= 1
HDF Spatial Parts= 1
HDF Use Max Rows=0
HDF Fixed Rows= 1
Calibration Method= 0
Calibration Iterations= 20
Calibration Max Change=0.05
Calibration Tolerance=0.2
Calibration Maximum=1.5
Calibration Minimum=0.5
Calibration Optimization Method= 1
WQ AD Non Conservative
WQ ULTIMATE=-1
WQ Max Comp Step=1HOUR
WQ Output Interval=15MIN
WQ Output Selected Increments= 0
WQ Output face flow=0
WQ Output face velocity=0
WQ Output face area=0
WQ Output face dispersion=0
WQ Output cell volume=0
WQ Output cell surface area=0
WQ Output cell continuity=0
WQ Output cumulative cell continuity=0
WQ Output face conc=0
WQ Output face dconc_dx=0
WQ Output face courant=0
WQ Output face peclet=0
WQ Output face adv mass=0
WQ Output face disp mass=0
WQ Output cell mass=0
WQ Output cell source sink temp=0
WQ Output nsm pathways=0
WQ Output nsm derived pathways=0
WQ Create Restart=0
WQ Fixed Restart=0
WQ System Summary=0
WQ Write To DSS=0
Sorting and Armoring Iterations= 10
XS Update Threshold= 0.02
Bed Roughness Predictor= 0
Hydraulics Update Threshold= 0.02
Energy Slope Method= 1
Volume Change Method= 1
Sediment Retention Method= 0
Sediment TS Multiplier= 1
Warm Up Method= 0
XS Weighting Method= 0
Number of US Weighted Cross Sections= 1
Number of DS Weighted Cross Sections= 1
Upstream XS Weight=0
Main XS Weight=1
Downstream XS Weight=0
Number of DS XS's Weighted with US Boundary= 1
Upstream Boundary Weight= 1
Weight of XSs Associated with US Boundary= 0
Number of US XS's Weighted with DS Boundary= 1
Downstream Boundary Weight= 0.5
Weight of XSs Associated with DS Boundary= 0.5
Percentile Method= 0
Sediment Output Level= 3
Mass or Volume Output= 0
Output Increment Type= 1
Profile and TS Output Increment= 1
Transport Output Increment 1
XS Output Flag= 0
XS Output Increment= 10
Read HDF5 Sediment Hotstart= 0
Sediment Hotstart Type= 0
Write Gradation File= 0
Read Gradation Hotstart= 0
Write HDF5 File= 1
Write Binary Output= 1
Write DSS Sediment File= 0
DSS Sediment Output Type= 1
SV Curve= 0
Specific Gage Flag= 0
Subcell Erosion Methods= 0
Subcell Deposition Methods= 0
Advection Scheme= 1
Matrix Solver= 0
Implicit Weighting Factor= 1
Maximum Outer Loop Convergence Iterations= 5
Convergence Maximum Absolute= 0.001
Convergence RMSE= 0.0001
Grain Fractions Max Abs Error= 0.001
Max Subgrid Regions= 1
Max Subgrid Length Scale= 3.402823E+38
Initial Layer Thickness= 3.402823E+38
Min Layer Thickness= 3.402823E+38
Max Layer Thickness= 3.402823E+38
Number of Layers= 5

--- LAURELFKT1.f01 (steady flow) ---

Flow Title=Flow
Program Version=6.20
Number of Profiles= 1
Profile Names=P100yr
River Rch & RM=LAURELFKT1,Main,1227
     306
Boundary for River Rch & Prof#=LAURELFKT1,Main            , 1
Up Type= 0
Dn Type= 3
Dn Slope=0.028993
DSS Import GetInterval= 0
DSS Import GetPeak= 0
DSS Import FillOption= 0

--- LAURELFKT1.g01 (geometry) ---

Geom Title=Geometry
Program Version=6.20

River Reach=LAURELFKT1      ,Main
Reach XY= 30
2365605.77700002678761.4619999982365584.59600002678781.766000003
     2365563.829678788.6980000142365529.06200002678790.447000012
2365469.90500003678781.7769999952365450.15499999678784.457000002
2365403.28000003678808.6759999992365362.16100001678824.658000022
2365307.46800001678836.3670000142365264.54893301678840.151262765
      2365236.69678869.8230000142365198.29099999678872.141000018
     2365161.469678890.8990000192365108.55300003678891.794000015
      2365099.08678896.5610000042365090.04300003678911.150999993
2365079.81500004678917.425000012     2364947.221 678960.90200001
2364910.13400005678985.399000019     2364890.942679006.169000015
2364799.49499999679056.9360000192364786.55300002679073.216000021
2364791.45300002679110.7510000172364788.51699999679131.111000001
2364764.82000002679175.5559999942364731.05599999679197.930000007
2364710.02200001      679235.0442364704.74400002679318.387000009
2364718.07600002679359.2349999992364733.98998953679386.495228017

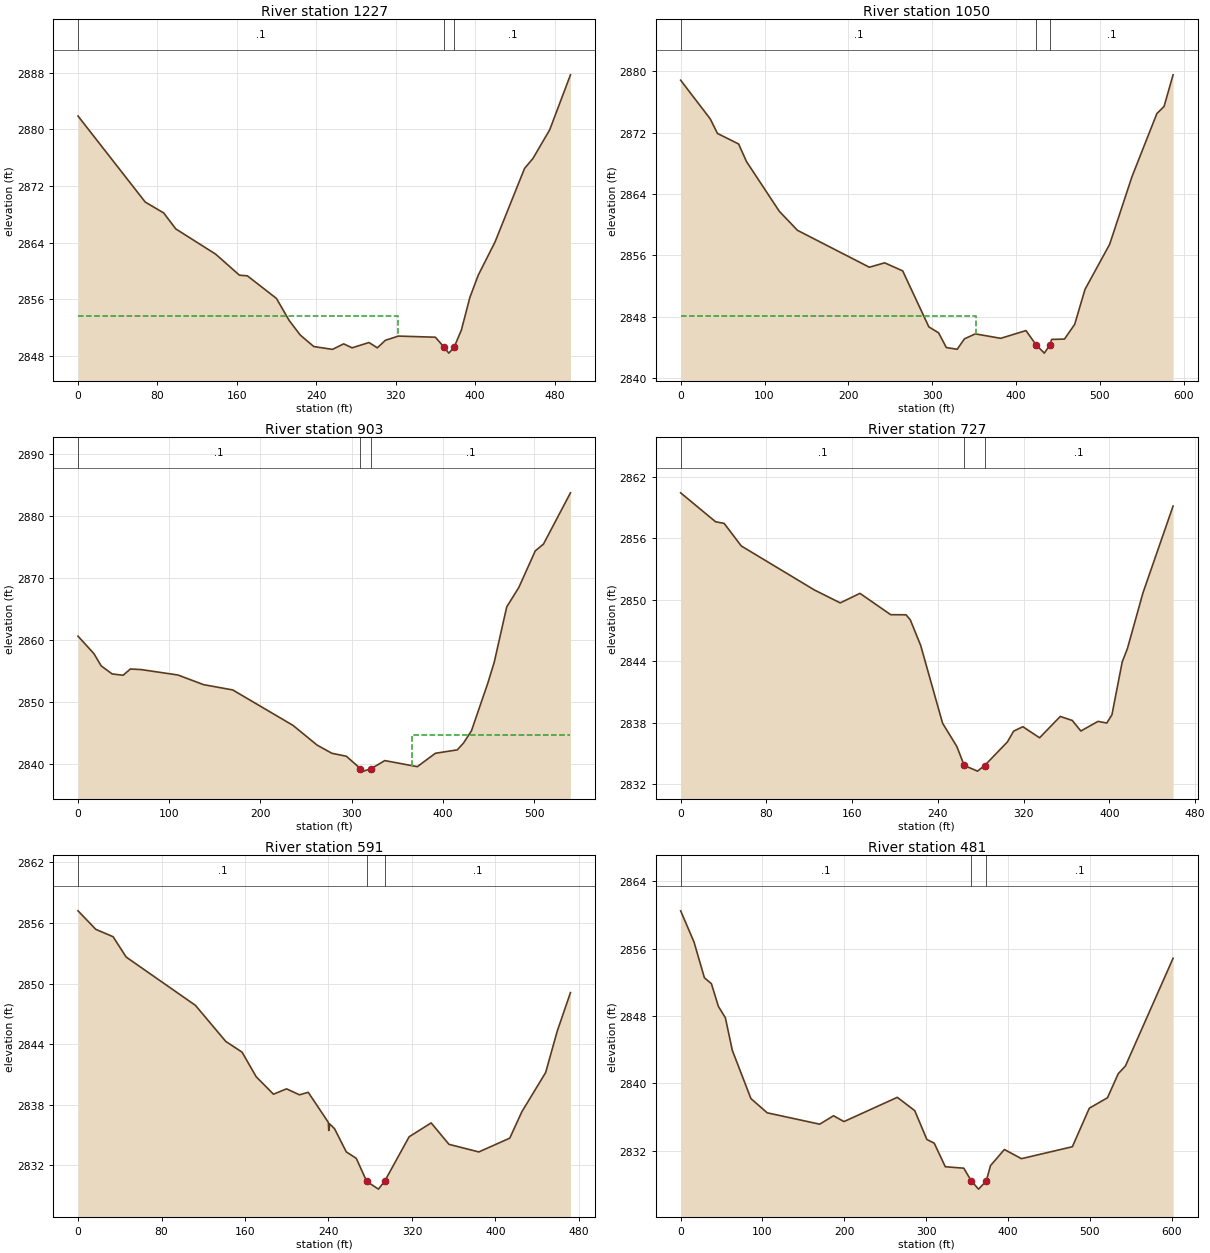
Type RM Length L Ch R = 1 ,1227    ,177.6,176.6,175
XS GIS Cut Line= 3
2365499.26633808678422.8178846592365508.94067537 678600.18073495
2365613.74599599678900.891385669
#Sta/Elev= 30
       0 2881.88    67.7 2869.72    86.3 2868.18    98.5 2865.92   138.6 2862.36
   162.6 2859.38   170.6 2859.29   199.9 2856.09   212.6    2853   223.9 2850.91
   237.5 2849.29   256.3 2848.89   267.6 2849.67   276.1 2849.11   293.1 2849.86
   301.5 2849.11   309.7 2850.18   322.7 2850.77     360 2850.61  368.87 2849.18
   373.5 2848.36   378.8 2849.17   386.2 2851.63   394.7 2856.22   403.2 2859.39
   420.1 2864.08   449.8 2874.47   458.3 2875.89   475.2 2879.95496.0775 2887.71
#Mann= 3 ,-1,0
       0      .1       0  368.87    .045       0   378.8      .1       0
#XS Ineff= 2 , 0
          322.22 2853.63
Permanent Ineff=
       F       F
Bank Sta=368.87,378.8
XS Rating Curve= 0 ,0
Exp/Cntr(USF)=0,0
Exp/Cntr=0.3,0.1

Type RM Length L Ch R = 1 ,1050    ,147.8,147.5,147.7
XS GIS Cut Line= 3
2365354.03944143678408.628479004 2365296.3119144 678546.97548344
2365463.52268235678951.068172654
#Sta/Elev= 30
       0 2878.82    35.3 2873.78    43.9 2871.88    69.1 2870.51    78.6  2868.2
   117.6 2861.74   139.3 2859.25     225 2854.44   243.3 2855.01   264.8 2853.96
     296 2846.66   307.6 2845.89   316.8 2843.97   329.8 2843.74   338.4  2845.1
   351.4 2845.75   381.7 2845.17   411.8 2846.18     424  2844.3   433.7 2843.24
  440.31  2844.3   442.4 2845.03   457.7 2845.07   469.9 2846.99   482.2 2851.55
   511.6 2857.43   538.2 2866.24   567.9 2874.47   576.5 2875.41587.2296 2879.52
#Mann= 3 ,-1,0
       0      .1       0     424    .045       0  440.31      .1       0
#XS Ineff= 2 , 0
          351.91 2848.11
Permanent Ineff=
       F       F
Bank Sta=424,440.31
XS Rating Curve= 0 ,0
Exp/Cntr(USF)=0,0
Exp/Cntr=0.3,0.1

Type RM Length L Ch R = 1 ,903     ,176.7,175.8,173.9
XS GIS Cut Line= 3
2365227.73790168 678535.839899382365216.09286605678752.616716401
 2365364.0848159679039.523969768
#Sta/Elev= 30
       0 2860.57    17.4 2857.76    25.4 2855.78    37.4 2854.48    49.4 2854.27
    57.4 2855.28    69.4 2855.18   109.5 2854.31   137.7 2852.75   169.6  2851.9
   235.7 2846.18   262.1    2843   278.3 2841.68   294.2  2841.2   309.6 2839.21
   313.2  2838.8   321.5 2839.21   336.3  2840.5     372 2839.52   391.8 2841.68
   415.8 2842.23   422.7 2843.34   431.4 2845.33   449.2 2852.96   456.3 2856.36
     470 2865.29   483.3 2868.44   501.3 2874.33   510.3 2875.43   539.9  2883.7
#Mann= 3 ,-1,0
       0      .1       0   309.6    .045       0   321.5      .1       0
#XS Ineff= 2 , 0
                          366.12         2844.56
Permanent Ineff=
       F       F
Bank Sta=309.6,321.5
XS Rating Curve= 0 ,0
Exp/Cntr(USF)=0,0
Exp/Cntr=0.3,0.1

Type RM Length L Ch R = 1 ,727     ,132.2,135.8,137.3
XS GIS Cut Line= 3
2365027.45686577678636.7155488212365039.62258677678795.398866197
 2365207.2979588679044.531674477
#Sta/Elev= 30
       0 2860.41    32.6 2857.59    40.6 2857.43    56.6 2855.23   124.8 2850.94
   148.9 2849.68   167.3 2850.61     196 2848.53   210.3 2848.52   214.3 2848.02
     224 2845.52   244.4 2837.95   257.7 2835.68   264.6 2833.83     277 2833.28
  283.61 2833.82   304.9 2836.13   310.7 2837.18   319.3 2837.61   334.9 2836.53
   354.2 2838.61   365.4 2838.22   373.4 2837.19   389.4 2838.13   397.6 2837.97
   402.4 2838.77     412 2843.93   416.8 2845.21   431.3 2850.64459.4525 2859.12
#Mann= 3 ,-1,0
       0      .1       0   264.6    .045       0  283.61      .1       0
Bank Sta=264.6,283.61
XS Rating Curve= 0 ,0
Exp/Cntr(USF)=0,0
Exp/Cntr=0.3,0.1

Type RM Length L Ch R = 1 ,591     ,111.3,110.4,108.5
XS GIS Cut Line= 4
2365021.55294144678676.8037989072364964.04659267678882.499584878
2365021.41831661679059.0395017392365073.37851421679109.819216778
#Sta/Elev= 30
       0 2857.19      17 2855.36    33.6 2854.63    46.1 2852.62   112.5 2847.84
   141.6 2844.27   157.2 2843.21   170.7 2840.78   187.3 2839.05   199.8 2839.58
   212.2 2838.99   220.6 2839.24   239.9 2836.26  240.28 2835.46   241.2 2836.11
   245.8 2835.64   257.1 2833.34   266.6 2832.71  276.68 2830.42   287.9 2829.66
  293.89 2830.45   317.3 2834.84   338.4 2836.21   355.5 2834.09   384.1 2833.34
   413.7  2834.7   425.4 2837.33   448.1 2841.19   459.2 2845.28   471.9  2849.1
#Mann= 3 ,-1,0
       0      .1       0  276.68    .045       0  293.89      .1       0
Bank Sta=276.68,293.89
XS Rating Curve= 0 ,0
Exp/Cntr(USF)=0,0
Exp/Cntr=0.3,0.1

Type RM Length L Ch R = 1 ,481     ,121.9,118.2,113.1
XS GIS Cut Line= 5
2364931.27139228678669.9020156922364842.44629563678910.287623793
2364845.54371084678913.6047315852364960.47402838679133.430680663
2365045.17819849679171.976676074
#Sta/Elev= 30
       0 2860.49   16.29  2856.8   29.08 2852.53   37.61 2851.83   46.14 2849.13
   54.67 2847.78   63.19  2843.9   85.92 2838.17  105.84 2836.48  169.99 2835.13
  186.86 2836.13  199.65 2835.44  264.84 2838.32  286.16 2836.74  300.98 2833.31
  309.98 2832.87  323.52 2830.07  346.09  2829.9   355.3 2828.38  364.14 2827.41
  373.55 2828.37  378.72  2830.2  395.74 2832.12  416.57 2831.03  478.82 2832.45
  499.56 2837.03  521.72 2838.27  534.91 2841.13   543.7 2842.05  601.93 2854.85
#Mann= 3 ,-1,0
       0      .1       0   355.3    .045       0  373.55      .1       0
Bank Sta=355.3,373.55
XS Rating Curve= 0 ,0
Exp/Cntr(USF)=0,0
Exp/Cntr=0.3,0.1

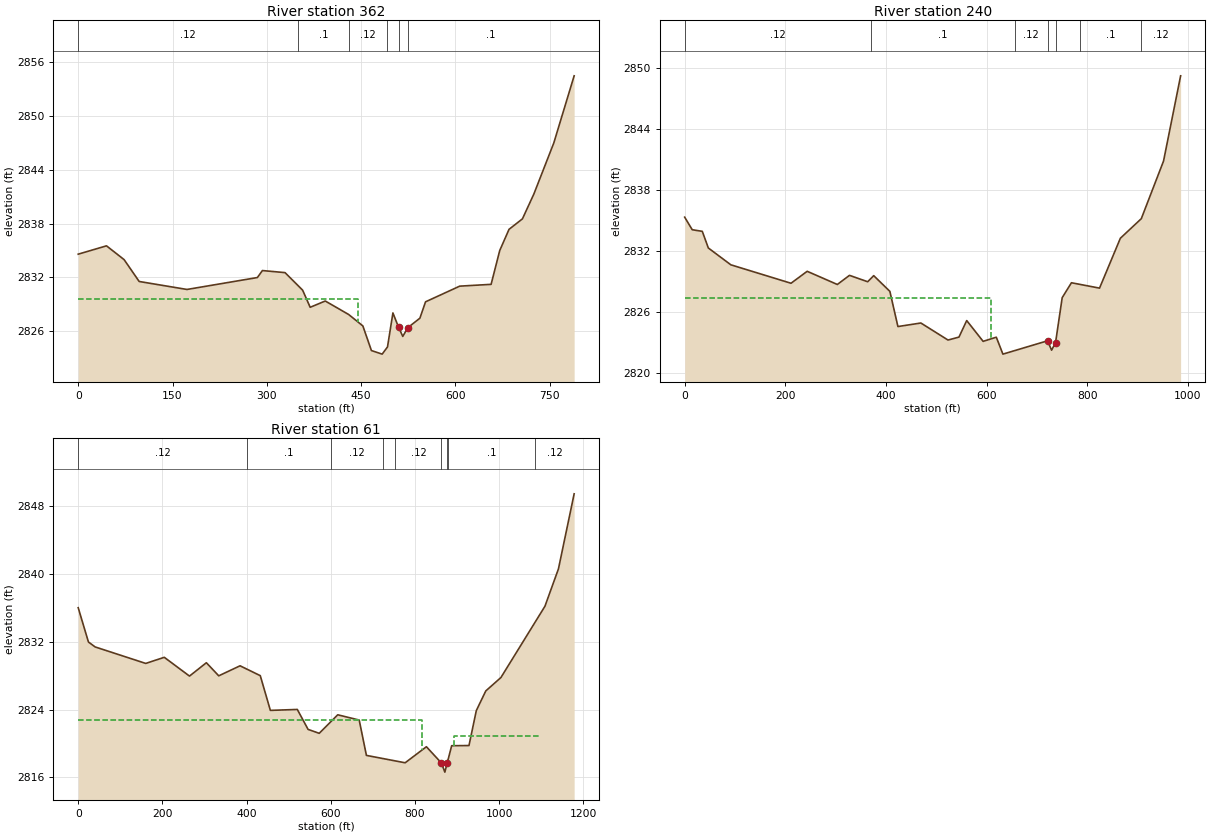
Type RM Length L Ch R = 1 ,362     ,122,122.9,121
XS GIS Cut Line= 3
2364698.44536225 678604.214686452364699.03421457 679014.94010829
2365032.75366356679192.753833448
#Sta/Elev= 30
       0  2834.6      45 2835.53      73 2833.99      97 2831.55     173 2830.66
     285 2831.99     293 2832.77     329 2832.54     357 2830.58     369 2828.67
     393 2829.37   430.1 2827.87   452.8 2826.59   466.4 2823.84   483.5 2823.44
     492 2824.24   500.6 2828.04   509.72826.424   516.3 2825.42   524.4  2826.4
   543.5 2827.45   552.5 2829.28   606.9 2831.03   656.8 2831.23   670.5    2835
   685.3 2837.37   706.6 2838.54   724.8 2841.31   756.5 2847.01   788.9 2854.51
#Mann= 6 ,-1,0
       0     .12       0     350      .1       0  430.73     .12       0
  490.73      .1       0   509.7    .045       0   524.4      .1       0
#XS Ineff= 2 , 0
          444.77 2829.59
Permanent Ineff=
       F       F
Bank Sta=509.7,524.4
XS Rating Curve= 0 ,0
Exp/Cntr(USF)=0,0
Exp/Cntr=0.3,0.1

Type RM Length L Ch R = 1 ,240     ,180,178.6,175.7
XS GIS Cut Line= 4
2364586.11446152 678582.222518322364556.50679624679087.456445634
2364926.86065351679249.0885087572365002.07654595679246.708258996
#Sta/Elev= 30
       0 2835.33      15 2834.09      35 2833.93      47 2832.29    91.7 2830.63
   211.3 2828.81   243.4 2829.99   303.3 2828.69   327.5 2829.59   363.6 2828.96
   375.6 2829.56   407.7 2828.01   423.7 2824.54   469.3 2824.89   523.2 2823.21
     545  2823.5   560.4 2825.13     593 2823.08   619.2 2823.49   632.3 2821.82
     7212823.135     729 2822.21   736.92822.948   750.1 2827.39   768.5 2828.86
   824.3 2828.33   865.7 2833.25   907.3 2835.18   951.5 2840.87   985.4 2849.27
#Mann= 7 ,-1,0
       0     .12       0     370      .1       0   656.1     .12       0
     721    .045       0   736.9     .12       0   786.1      .1       0
   906.1     .12       0
#XS Ineff= 2 , 0
          608.38 2827.36
Permanent Ineff=
       F       F
Bank Sta=721,736.9
XS Rating Curve= 0 ,0
Exp/Cntr(USF)=0,0
Exp/Cntr=0.3,0.1

Type RM Length L Ch R = 1 ,61      ,,,
XS GIS Cut Line= 6
2364541.16191039678552.8511208052364529.15602435 679175.95660591
2364680.78630634679329.9480181152364726.49755003679332.850319302
2364833.78879598679277.618222364 2365005.4001578679290.574135011
#Sta/Elev= 30
       0 2835.99    24.3 2831.95    40.3 2831.37   160.4 2829.43   204.4 2830.15
   264.3 2827.94   304.4 2829.51   333.8 2827.97   384.4 2829.15   432.4 2827.99
   456.4  2823.9   520.4 2824.01     546 2821.66   572.4  2821.2   616.4 2823.38
   667.4 2822.76   684.5  2818.6   776.5 2817.73     827 2819.62   862.72817.703
   870.8 2816.63   876.52817.721     887 2819.74   928.1 2819.76   945.5 2823.87
     968 2826.19    1004 2827.77  1108.5 2836.16  1140.6 2840.56  1177.9  2849.4
#Mann= 9 ,-1,0
       0     .12       0     400      .1       0     600     .12       0
  723.22      .1       0  753.22     .12       0   862.7    .045       0
   876.5     .12       0  879.33      .1       0 1085.81     .12       0
#XS Ineff= 2 ,-1
       0  817.182822.777  893.16 1098.362820.884
Permanent Ineff=
       F       F
Bank Sta=862.7,876.5
XS Rating Curve= 0 ,0
Exp/Cntr(USF)=0,0
Exp/Cntr=0.3,0.1
LCMann Table=0

Chan Stop Cuts=-1
Use User Specified Reach Order=0
Composite Channel Slope=5